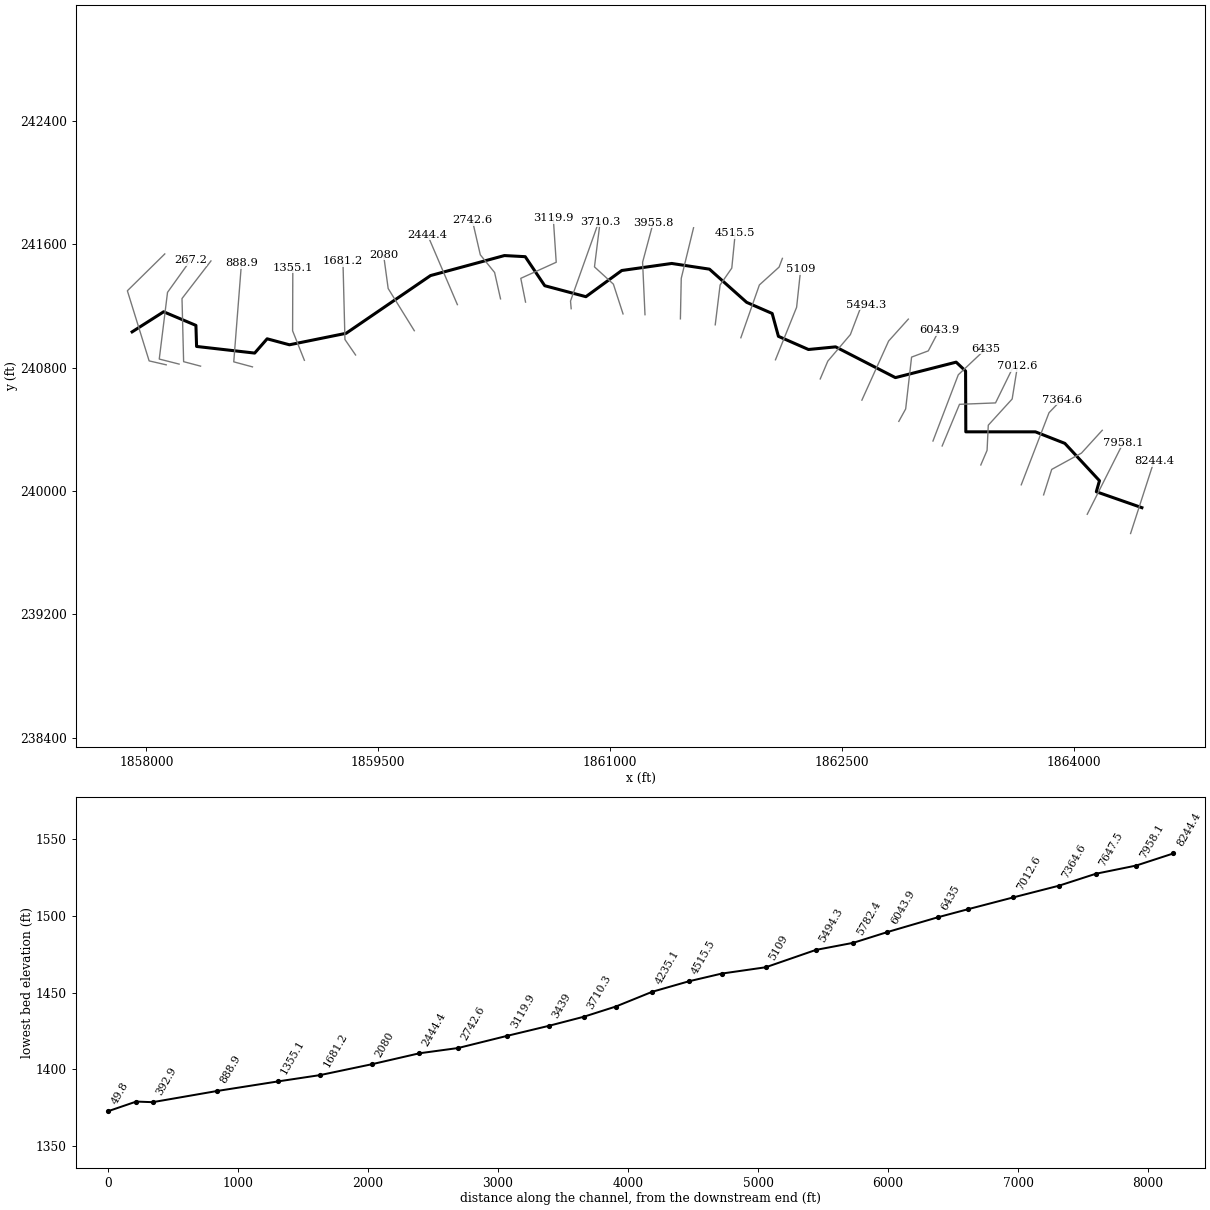
--- JIMMYRN.prj (project) ---

Proj Title=JIMMYRN
Current Plan=p01
Default Exp/Contr=0,0
English Units
Geom File=g01
Flow File=f01
Plan File=p01
BEGIN DESCRIPTION:
END DESCRIPTION:
DSS Export Rating Curves= 0
DSS Export Rating Curve Sorted= 0
DSS Export Volume Flow Curves= 0
DXF OffsetX= 0
DXF OffsetY= 0
DXF ScaleX= 0
DXF ScaleY= 0

--- JIMMYRN.p01 (plan) ---

Plan Title=Floodplain
Program Version=4.00
Geom File=g01
Flow File=f01
K Sum by GR=0
Std Step Tol=0.01
Critical Tol=0.01
Num of Std Step Trials=20
Max Error Tol=0.3
Flow Tol Ratio=0.001
Split Flow NTrial=30
Split Flow Tol=0.02
Split Flow Ratio=0.02
Log Output Level=0
Friction Slope Method=1
Unsteady Friction Slope Method=2
Unsteady Bridges Friction Slope Method=1
Global Log Level=0
CheckData=False
Run HTab=0
Run UNet=0
Run PostProcess=0
UNET Theta=0
UNET Theta Warmup=0
UNET ZTol=0
UNET ZSATol=0
UNET MxIter=0
UNET MaxInSteps=0
UNET DtIC=0
UNET DtMin=0
UNET MaxCRTS=0
UNET WFStab=0
UNET SFStab=0
UNET WFX=0
UNET SFX=0
UNET DSS MLevel=0
UNET DZMax Abort=0
UNET Convert EG Bridges=0
UNET Use Existing IB Tables=0
UNET Froude Limit=0
UNET Froude Power=0
Write IC File=0
Echo Input=False
Echo Output=False
Write Detailed=0

--- JIMMYRN.f01 (steady flow) ---

Flow Title=NFF Regression Equation
Program Version=5.03
Number of Profiles= 1
Profile Names=P100yr
River Rch & RM=JIMMYRN,Main            ,8244.4
512.5307
River Rch & RM=JIMMYRN,Main            ,5109
 556.027
River Rch & RM=JIMMYRN,Main            ,4769.8
661.9617
River Rch & RM=JIMMYRN,Main            ,392.9
724.2882
River Rch & RM=JIMMYRN,Main            ,267.2
726.5309
Boundary for River Rch & Prof#=JIMMYRN,Main            , 1
Up Type= 0
Dn Type= 3
Dn Slope=0.01473
DSS Import GetInterval= 0
DSS Import GetPeak= 0
DSS Import FillOption= 0

--- JIMMYRN.g01 (geometry) ---

Geom Title=USGS 10m DEM
Program Version=5.03

River Reach=JIMMYRN         ,Main
Reach XY= 30
     1864438.417      239891.729     1864143.708      239994.877
     1864164.083      240066.446     1863940.124      240308.416
     1863750.057        240383.1     1863299.672      240383.258
     1863298.151      240777.054     1863237.217      240834.767
     1862844.366      240734.519     1862457.659      240933.778
     1862281.901       240916.77     1862087.717      241002.115
     1862047.318      241150.185     1861882.354      241222.248
      1861641.67      241437.432     1861397.534        241474.3
     1861074.627      241428.678     1860842.723      241258.972
     1860576.494       241330.05     1860450.265      241518.238
     1860315.784       241525.52     1859837.874      241395.829
     1859291.864      241021.728     1858925.324      240947.277
      1858781.08      240986.041     1858700.537       240893.54
     1858324.799      240936.503     1858320.552      241072.968
     1858111.783      241161.166     1857907.997      241031.054

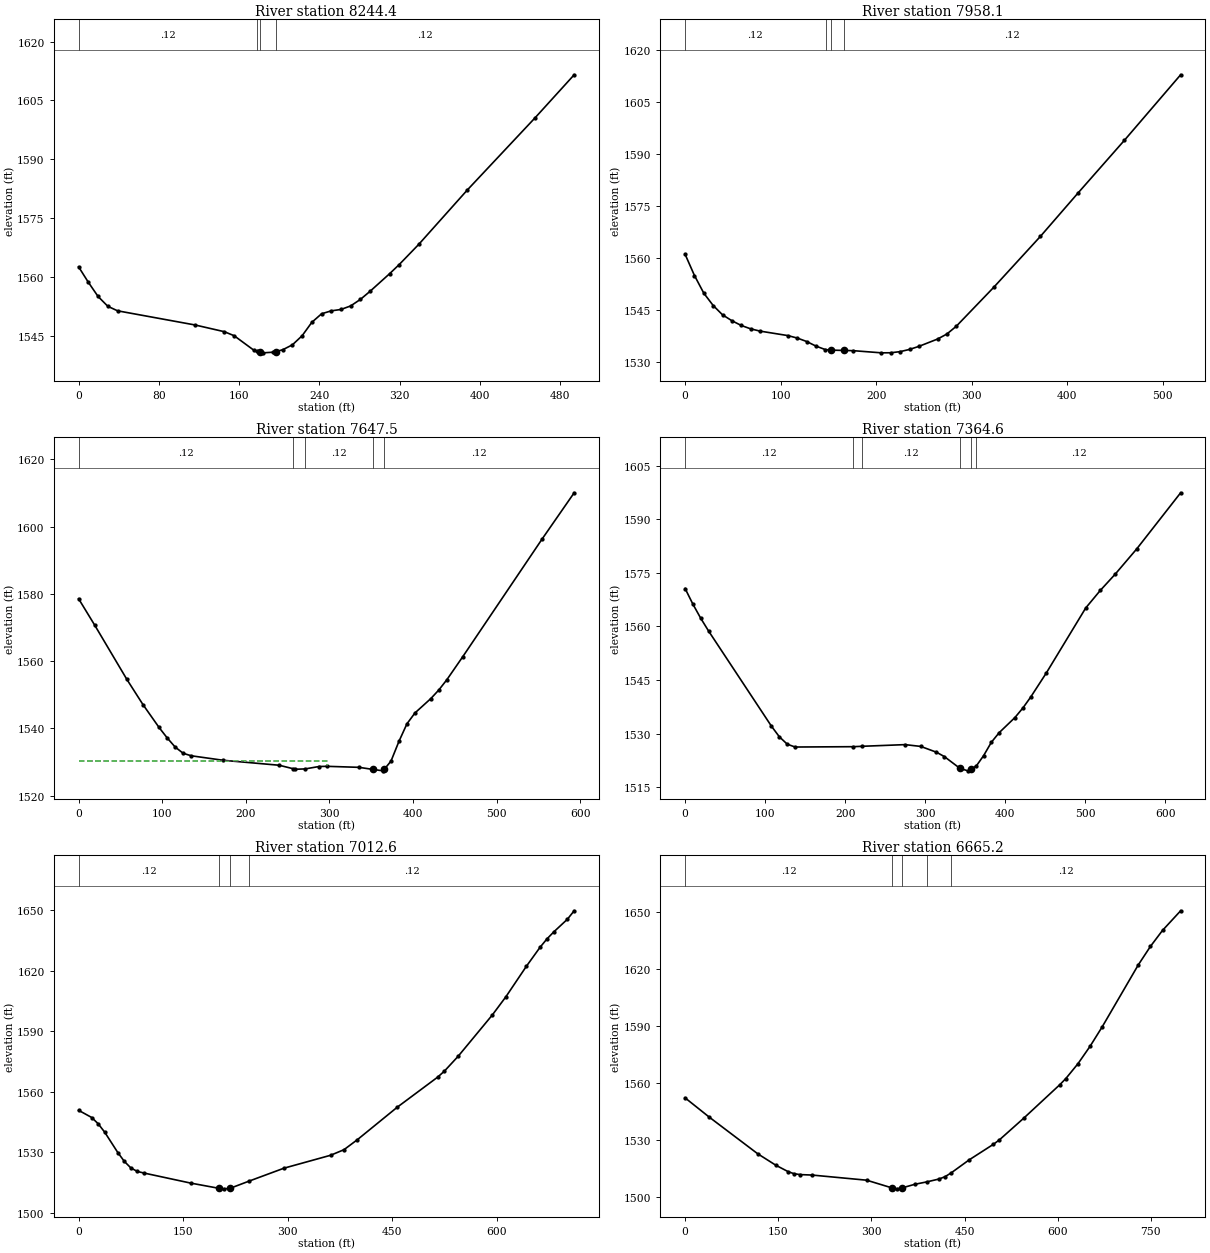
Type RM Length L Ch R = 1 ,8244.4  ,289.2,286.3,325.2
XS GIS Cut Line= 2
     1864365.285      239724.251     1864517.228      240194.314
#Sta/Elev= 30
       0 1562.56     9.7 1558.63    19.4 1555.01    29.1 1552.51    38.8 1551.36
   116.2 1547.74   145.3 1546.03     155 1545.01   174.4 1541.36   177.4 1541.14
  180.59 1540.87     184 1540.64   193.7  1540.8   196.7 1540.97   203.4 1541.42
   213.1 1542.68   222.8    1545   232.5 1548.43   242.2  1550.6   251.8 1551.35
   261.5  1551.7   271.2 1552.61   280.9 1554.27   290.6 1556.35     310 1560.82
   319.6 1563.16     339 1568.29   387.5 1582.18   455.3 1600.66     494 1611.56
#Mann= 4 ,-1 , 0
       0     .12       0   177.4    .045       0  180.59    .045       0
   196.7     .12       0
Bank Sta=180.59,196.7
XS Rating Curve= 0 ,0
Exp/Cntr=0.3,0.1

Type RM Length L Ch R = 1 ,7958.1  ,324.1,310.6,251
XS GIS Cut Line= 2
     1864084.959       239849.02      1864318.04      240312.581
#Sta/Elev= 30
       0 1561.09     9.8 1554.98    19.6 1549.89    29.4 1546.35    39.2 1543.67
      49 1541.97    58.7 1540.62    68.5 1539.65    78.3 1538.99   107.7 1537.69
   117.5 1536.98   127.3 1535.99   137.1 1534.66   146.8 1533.67  152.66 1533.51
   166.4 1533.42   176.2 1533.35   205.6 1532.73   215.4 1532.75   225.2 1533.08
     235 1533.71   244.8 1534.59   264.3 1536.69   274.1 1538.14   283.9 1540.36
   323.1 1551.56     372 1566.22   411.2 1578.64   460.1 1593.91   518.9 1612.74
#Mann= 4 ,-1 , 0
       0     .12       0   147.2    .045       0  152.66    .045       0
   166.4     .12       0
Bank Sta=152.66,166.4
XS Rating Curve= 0 ,0
Exp/Cntr=0.3,0.1

Type RM Length L Ch R = 1 ,7647.5  ,266.7,282.9,298.5
XS GIS Cut Line= 4
     1863802.735      239974.634     1863855.129      240139.603
     1864047.547      240245.336     1864182.099      240393.296
#Sta/Elev= 30
       0 1578.53    19.2  1570.7    57.7 1554.56    76.9 1547.09    96.2 1540.27
   105.8  1537.2   115.4 1534.46     125  1532.6   134.6 1531.86   173.1 1530.51
   239.9 1529.04   255.81528.055     259 1527.85   270.8 1527.95   287.6 1528.67
   297.2 1528.72   335.4 1528.42  351.94  1527.8     364 1527.38  365.52 1527.83
   373.6  1530.3   383.1 1536.17   392.6 1541.35   402.2 1544.59   421.2 1548.87
   430.7 1551.41   440.3 1554.45   459.3 1561.29   554.5 1596.39   592.6 1610.05
#Mann= 5 ,-1 , 0
       0     .12       0   255.8    .045       0   270.8     .12       0
  351.94    .045       0  365.52     .12       0
#XS Ineff= 2 , 0
          297.51 1530.35
Permanent Ineff=
       F       F
Bank Sta=351.94,365.52
XS Rating Curve= 0 ,0
Exp/Cntr=0.3,0.1

Type RM Length L Ch R = 1 ,7364.6  ,344.4,352,358.9
XS GIS Cut Line= 3
     1863658.209      240039.822     1863837.706      240506.981
     1863919.767      240592.628
#Sta/Elev= 30
       0 1570.61     9.8 1566.21    19.6 1562.26    29.4  1558.7   107.9  1532.1
   117.8 1529.13   127.6 1527.08   137.4 1526.28  210.051526.374  220.691526.479
   274.8 1526.95   294.4 1526.45     314 1524.83   323.8 1523.62   343.4 1520.31
   353.3 1519.62   357.5 1520.12   363.9 1521.01   372.9 1523.85   382.7 1527.63
   392.5 1530.32   412.1 1534.53     422 1537.19   431.8 1540.26   451.4 1547.03
   500.5 1565.16   518.7 1570.07     537 1574.53   564.3  1581.7   619.1 1597.38
#Mann= 6 ,-1 , 0
       0     .12       0  210.05     .06       0  220.69     .12       0
   343.4    .045       0   357.5    .045       0   363.9     .12       0
Bank Sta=343.4,357.5
XS Rating Curve= 0 ,0
Exp/Cntr=0.3,0.1

Type RM Length L Ch R = 1 ,7012.6  ,380.9,347.5,311.3
XS GIS Cut Line= 5
     1863396.679      240168.477      1863437.16      240263.301
     1863444.972      240426.062      1863599.42      240596.024
     1863633.774      240808.874
#Sta/Elev= 30
       0 1550.84    18.8 1547.29    28.1 1544.17    37.5 1539.99    56.2 1529.96
    65.6 1525.57      75 1522.32    84.4 1520.57    93.7 1519.81   160.6 1514.84
     202  1512.2   208.5 1511.98     217 1512.19  244.841515.828   294.8 1522.21
   361.7  1528.6   380.9 1531.36     400 1536.28   457.4  1552.4   515.3 1567.26
   525.1 1570.27   544.7 1577.57   593.7 1597.99   613.3 1607.06   642.7 1622.14
   662.3 1631.53   672.1 1635.64   681.9 1639.12   701.5 1645.41   711.3 1649.62
#Mann= 4 ,-1 , 0
       0     .12       0     202    .045       0     217    .016       0
  244.84     .12       0
Bank Sta=202,217
XS Rating Curve= 0 ,0
Exp/Cntr=0.3,0.1

Type RM Length L Ch R = 1 ,6665.2  ,213.6,230.1,246.3
XS GIS Cut Line= 4
     1863146.625      240291.488     1863258.774      240561.478
     1863491.847      240570.593     1863611.639      240815.385
#Sta/Elev= 30
       0 1552.18      39 1542.02   116.9 1522.77   146.2 1516.71   165.7 1513.39
   175.4 1512.26   185.2  1511.8   204.6 1511.55   292.4 1508.85   333.9 1504.72
     341  1504.3   348.9 1504.75   370.1  1506.7  388.931507.934     409 1509.47
   418.7  1510.7  428.761512.747   457.6 1519.57   496.4 1527.71   506.2 1530.07
   545.1  1541.4   603.5 1559.11   613.2 1562.35   632.7 1570.14   652.1 1579.26
   671.6 1589.47     730 1622.23   749.5 1631.92   768.9 1640.32   798.1 1650.65
#Mann= 5 ,-1 , 0
       0     .12       0   333.9    .045       0   348.9     .12       0
  388.93    .016       0  428.76     .12       0
Bank Sta=333.9,348.9
XS Rating Curve= 0 ,0
Exp/Cntr=0.3,0.1

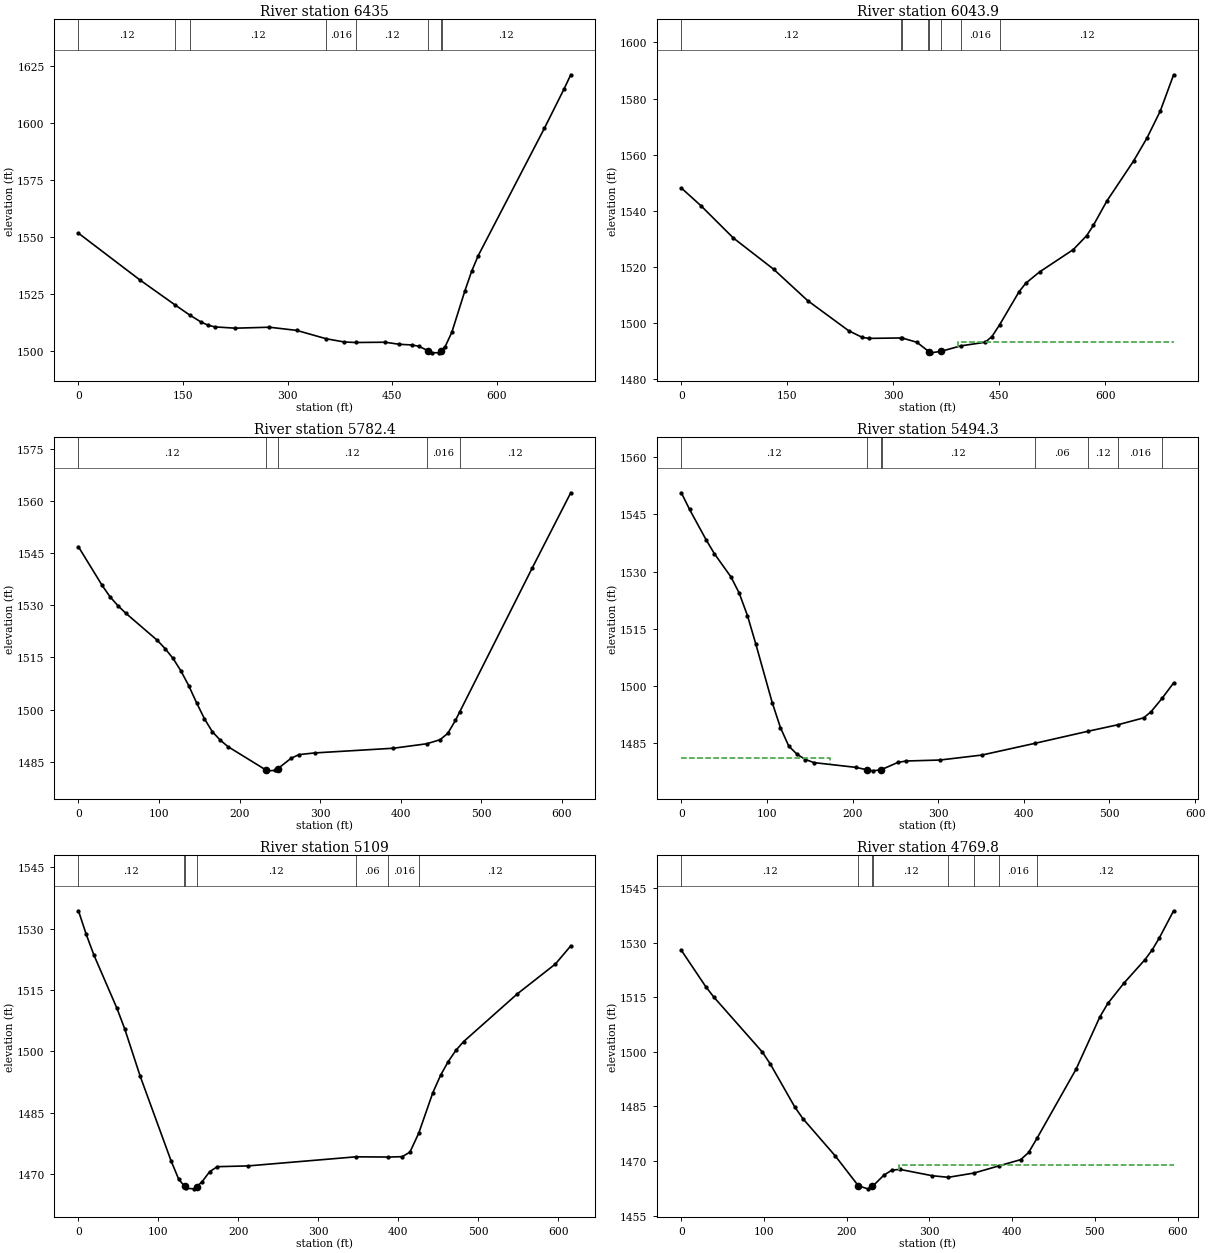
Type RM Length L Ch R = 1 ,6435    ,374.6,391.2,406.6
XS GIS Cut Line= 3
     1863087.254      240323.676     1863250.962      240752.885
     1863430.006      240922.051
#Sta/Elev= 30
       0 1551.53      88 1531.06  138.611520.068  159.731515.607   175.9 1512.57
   185.7 1511.22   195.5 1510.46   224.8  1509.9   273.7 1510.32   312.8 1508.93
  355.33 1505.25   381.2 1503.84  397.631503.626   439.8 1503.74   459.4 1502.86
   478.3 1502.53   487.8 1501.98  501.47 1499.98   506.7 1499.17   516.2 1499.09
  519.14 1499.91   520.8 1500.43   525.7 1501.85   535.2 1508.07   554.1 1526.39
   563.6  1534.8   573.1 1541.72   667.8 1597.46   696.2 1614.81   705.7 1620.98
#Mann= 8 ,-1 , 0
       0     .12       0  138.61     .06       0  159.73     .12       0
  355.33    .016       0  397.63     .12       0  501.47    .045       0
  519.14    .045       0   520.8     .12       0
Bank Sta=501.47,519.14
XS Rating Curve= 0 ,0
Exp/Cntr=0.3,0.1

Type RM Length L Ch R = 1 ,6043.9  ,268.4,261.5,253.3
XS GIS Cut Line= 5
     1862866.388       240450.98     1862910.692      240531.579
     1862948.879      240867.468     1863056.952      240907.833
     1863127.426      241041.734
#Sta/Elev= 30
       0 1548.11    27.6 1541.84    73.6 1530.31   130.6 1519.18   178.9 1507.97
   236.8 1497.27   256.2 1494.88   265.8 1494.54  310.181494.689  312.721494.657
   333.4 1493.15   348.5 1490.18   350.5 1489.77   352.8 1489.39  367.27 1489.91
  395.621491.877     430 1493.16   439.6  1495.2  450.611499.455   478.1 1511.22
   487.7 1514.25   506.9  1518.2   554.8 1526.19   573.8 1531.19   583.2 1534.85
   602.1 1543.43     640 1557.73   658.9 1565.88   677.8 1575.52   696.7 1588.46
#Mann= 8 ,-1 , 0
       0     .12       0  310.18     .06       0  312.72     .12       0
   348.5    .045       0   350.5    .045       0  367.27     .12       0
  395.62    .016       0  450.61     .12       0
#XS Ineff= 2 , 0
                          392.26         1493.18
Permanent Ineff=
       F       F
Bank Sta=350.5,367.27
XS Rating Curve= 0 ,0
Exp/Cntr=0.3,0.1

Type RM Length L Ch R = 1 ,5782.4  ,293.9,288.1,281.6
XS GIS Cut Line= 3
      1862627.57      240588.632     1862800.441      240971.635
     1862927.881      241113.639
#Sta/Elev= 30
       0 1546.81    29.3 1535.75    39.1 1532.47    48.9  1529.9    58.6 1527.75
    97.7 1519.95   107.5 1517.56   117.3 1514.75     127  1511.2   136.8 1506.92
   146.6 1501.97   156.4 1497.36   166.1 1493.66   175.9 1491.25   185.7 1489.34
   232.2 1482.71   234.5  1482.4   244.3 1482.52   247.2 1482.98   263.8 1485.99
   273.6 1487.06   293.2 1487.55   390.9  1488.9  432.341490.186   448.8 1491.35
   458.4 1493.18   467.9 1496.91  473.131499.321   563.3 1540.77     611 1562.35
#Mann= 5 ,-1 , 0
       0     .12       0   232.2    .045       0   247.2     .12       0
  432.34    .016       0  473.13     .12       0
Bank Sta=232.2,247.2
XS Rating Curve= 0 ,0
Exp/Cntr=0.3,0.1

Type RM Length L Ch R = 1 ,5494.3  ,377.2,385.2,391.9
XS GIS Cut Line= 5
     1862358.128      240726.046     1862407.212      240841.426
     1862553.045      241013.301     1862613.892      241173.591
     1862653.876      241207.921
#Sta/Elev= 30
       0 1550.65     9.6 1546.29    28.9 1538.34    38.6 1534.68    57.9 1528.61
    67.5 1524.39    77.2 1518.46    86.8 1511.14   106.1 1495.67   115.7 1489.12
   125.4 1484.27   135.2 1482.09     145 1480.73   154.8 1479.92   203.8 1478.67
  217.23 1478.02   223.4 1477.76   233.2 1478.03   234.4 1478.15   252.8 1479.96
   262.6 1480.34   301.8 1480.59   350.8 1481.89  412.551484.952  475.291488.155
  510.371489.865   539.8 1491.64   548.6 1493.26  561.711496.843   574.9 1500.81
#Mann= 8 ,-1 , 0
       0     .12       0  217.23    .045       0   233.2    .045       0
   234.4     .12       0  412.55     .06       0  475.29     .12       0
  510.37    .016       0  561.71     .12       0
#XS Ineff= 2 , 0
          173.99  1481.1
Permanent Ineff=
       F       F
Bank Sta=217.23,233.2
XS Rating Curve= 0 ,0
Exp/Cntr=0.3,0.1

Type RM Length L Ch R = 1 ,5109    ,337.6,339.3,339.3
XS GIS Cut Line= 3
     1862068.697      240850.088     1862205.389      241190.385
     1862231.916       241437.97
#Sta/Elev= 30
       0 1534.34     9.6 1528.64    19.3 1523.54    48.2  1510.5    57.9 1505.49
    77.2 1493.96   115.8 1473.32   125.5 1468.75   132.2 1467.24  132.92 1467.06
   135.1 1466.59   144.8 1466.47  147.92 1467.03   154.4 1468.15   164.1 1470.67
   173.7 1471.88   212.3 1472.07  347.061474.286  387.751474.228     405 1474.32
   414.6 1475.44  425.561480.048   443.3 1489.98   452.9 1494.18   462.5 1497.55
   472.1 1500.28   481.6 1502.39   548.7 1514.03   596.6 1521.36   615.7 1525.77
#Mann= 7 ,-1 , 0
       0     .12       0   132.2    .045       0  132.92    .045       0
  147.92     .12       0  347.06     .06       0  387.75    .016       0
  425.56     .12       0
Bank Sta=132.92,147.92
XS Rating Curve= 0 ,0
Exp/Cntr=0.3,0.1

Type RM Length L Ch R = 1 ,4769.8  ,260.2,254.2,247.9
XS GIS Cut Line= 4
     1861844.777      240992.841     1861964.504      241334.916
     1862092.108      241450.801     1862113.478      241507.279
#Sta/Elev= 30
       0 1527.98    29.4 1518.01    39.2 1515.13      98 1499.97   107.8  1496.6
   137.1 1484.88   146.9 1481.68   186.1  1471.4  214.01 1463.19   225.3 1462.34
  230.52 1463.03   232.1 1463.24   244.9  1466.1   254.7  1467.5   264.5 1467.68
   303.6 1465.94  322.871465.513  353.981466.693   384.1 1468.67   410.3 1470.37
   419.9 1472.34  430.491476.434   477.3 1495.28   506.1 1509.68   515.6 1513.34
   534.8 1518.85   560.7 1525.44   569.3 1528.09   577.9 1531.37   595.2 1538.85
#Mann= 8 ,-1 , 0
       0     .12       0  214.01    .045       0  230.52    .045       0
   232.1     .12       0  322.87     .06       0  353.98     .12       0
   384.1    .016       0  430.49     .12       0
#XS Ineff= 2 , 0
                          263.16         1468.92
Permanent Ineff=
       F       F
Bank Sta=214.01,230.52
XS Rating Curve= 0 ,0
Exp/Cntr=0.3,0.1

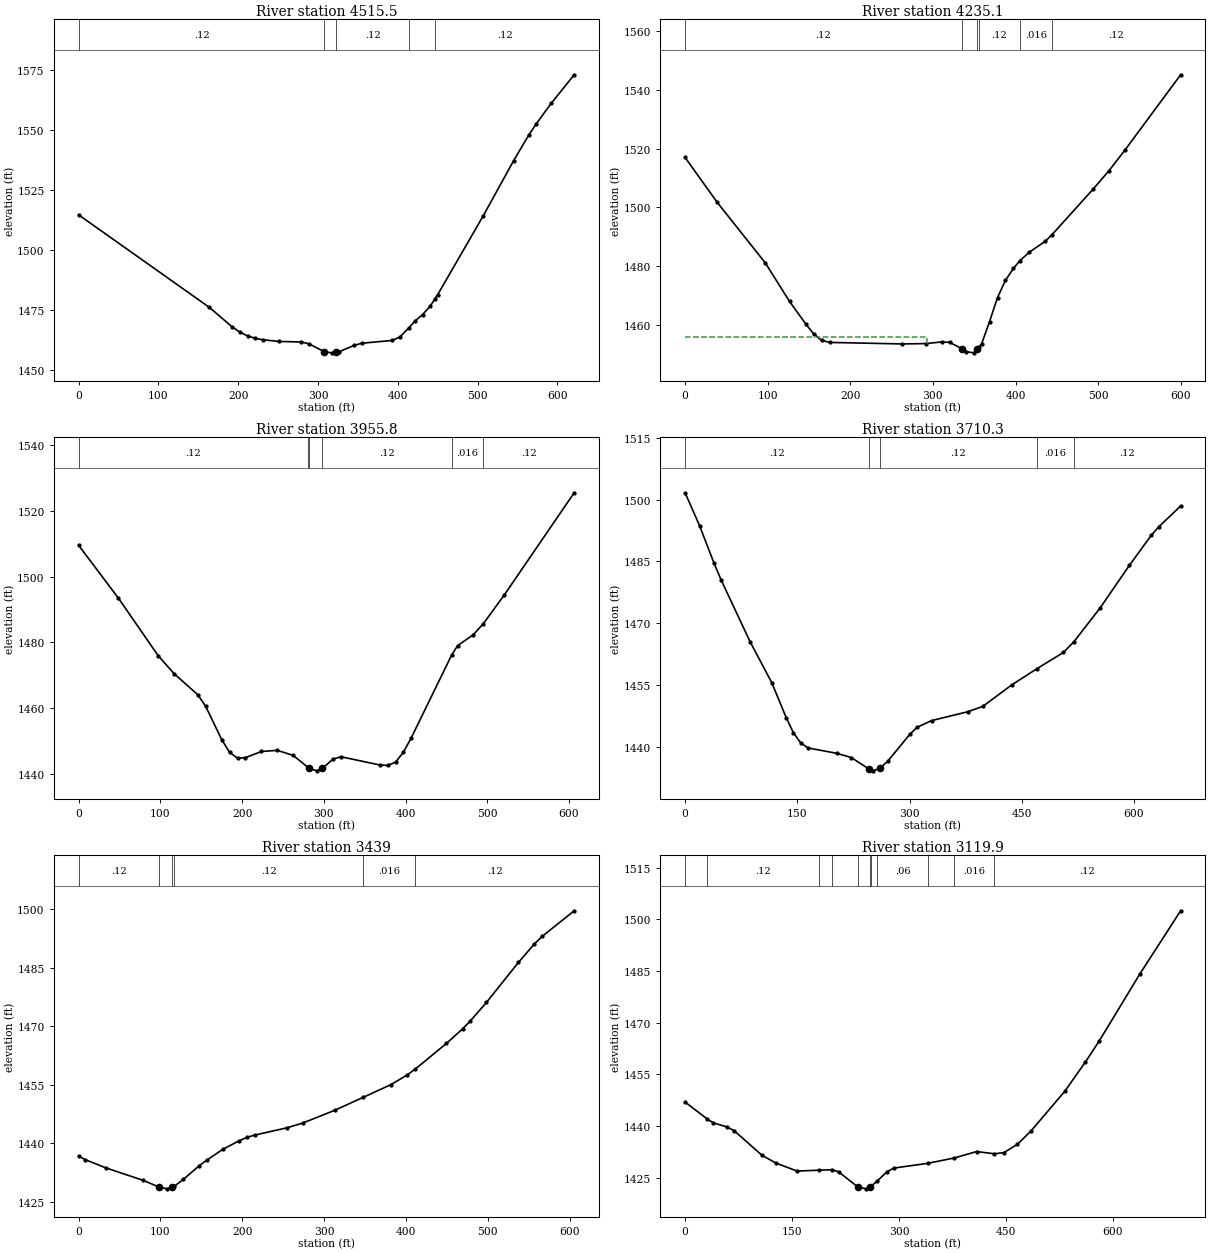
Type RM Length L Ch R = 1 ,4515.5  ,271.9,280.5,288.6
XS GIS Cut Line= 4
       1861679.1      241076.636     1861710.597      241334.916
     1861786.118      241444.291      1861808.57      241671.167
#Sta/Elev= 30
       0 1514.79   163.8 1476.24   192.7 1468.02   202.4 1465.86     212 1464.31
   221.6 1463.31   231.3 1462.73   250.6 1462.02   279.2 1461.81   288.7 1461.04
   307.9 1457.76   317.2 1457.28   322.9 1457.58   326.6 1457.78   345.6 1460.42
   355.1 1461.28   393.1 1462.46   402.6 1463.86  414.281467.823   421.6 1470.52
   431.1 1473.24   440.6  1476.7  446.411479.684   450.1 1481.58   507.1 1514.36
   545.1 1537.32   564.1    1548   573.6 1552.73   592.6 1561.38   621.1 1573.17
#Mann= 5 ,-1 , 0
       0     .12       0   307.9    .045       0   322.9     .12       0
  414.28    .016       0  446.41     .12       0
Bank Sta=307.9,322.9
XS Rating Curve= 0 ,0
Exp/Cntr=0.3,0.1

Type RM Length L Ch R = 1 ,4235.1  ,272.6,279.3,285.6
XS GIS Cut Line= 3
     1861453.808      241115.396     1861459.295      241377.885
     1861538.904      241705.685
#Sta/Elev= 30
       0 1517.01    38.9 1501.71    97.2 1481.07   126.4 1467.99   145.9 1460.37
   155.6 1456.93   165.3 1454.71     175 1454.02   262.6  1453.5   291.5 1453.62
   310.7 1454.19   320.4 1454.02  334.82 1451.91   339.6 1450.91   349.3 1450.47
  353.35 1451.83   355.7 1452.48   358.9 1453.49   368.6 1461.14   378.2 1469.29
   387.8 1475.14   397.5 1479.25  405.141481.821   416.8 1484.78     436 1488.46
  443.911490.637   493.9 1506.21   513.1 1512.49   532.4 1519.51   599.9 1545.18
#Mann= 6 ,-1 , 0
       0     .12       0  334.82    .045       0  353.35    .045       0
   355.7     .12       0  405.14    .016       0  443.91     .12       0
#XS Ineff= 2 , 0
          292.26 1456.01
Permanent Ineff=
       F       F
Bank Sta=334.82,353.35
XS Rating Curve= 0 ,0
Exp/Cntr=0.3,0.1

Type RM Length L Ch R = 1 ,3955.8  ,227.7,245.5,263.2
XS GIS Cut Line= 3
     1861224.831        241142.2     1861209.295      241482.051
     1861278.093      241739.068
#Sta/Elev= 30
       0 1509.53    48.6 1493.48    97.2 1475.98   116.6 1470.51   145.8 1464.05
   155.5  1460.5     175  1450.4   184.7  1446.5   194.4 1444.74   204.1  1444.9
   223.6 1446.77     243 1447.11   262.4 1445.61   280.7  1441.9   281.9 1441.64
   291.6 1440.88  298.32 1441.66     311  1444.4   320.8 1445.18   368.7 1442.65
   378.2 1442.52   387.7 1443.52   397.2 1446.49   406.7 1450.78  456.281476.079
   463.7    1479   482.7 1482.28  495.251485.705   520.8 1494.42   606.3 1525.53
#Mann= 6 ,-1 , 0
       0     .12       0   280.7    .045       0   281.9    .045       0
  298.32     .12       0  456.28    .016       0  495.25     .12       0
Bank Sta=281.9,298.32
XS Rating Curve= 0 ,0
Exp/Cntr=0.3,0.1

Type RM Length L Ch R = 1 ,3710.3  ,298,271.3,244.5
XS GIS Cut Line= 4
     1861082.818      241147.333     1861020.493      241340.124
     1860898.097      241452.103     1860934.556       241743.77
#Sta/Elev= 30
       0 1501.65    19.3 1493.69    38.6 1484.62    48.2 1480.51    86.8 1465.57
   115.8 1455.63   135.1 1447.16   144.7  1443.5   154.4 1441.05     164 1439.81
   202.6 1438.49   222.1 1437.47   245.4 1434.71   251.4 1434.24   260.4 1434.88
   270.9 1436.57   300.2 1443.06     310 1444.79   329.5 1446.42   378.3 1448.59
   397.9 1449.86   437.1 1455.13  470.141458.983   505.7 1462.94  519.641465.519
   554.7 1473.71   593.9 1484.06   623.2 1491.35     633 1493.37   662.4 1498.44
#Mann= 5 ,-1 , 0
       0     .12       0   245.4    .045       0   260.4     .12       0
  470.14    .016       0  519.64     .12       0
Bank Sta=245.4,260.4
XS Rating Curve= 0 ,0
Exp/Cntr=0.3,0.1

Type RM Length L Ch R = 1 ,3439    ,336,319,300.4
XS GIS Cut Line= 3
     1860747.452      241181.101     1860743.149      241230.749
     1860929.347      241754.187
#Sta/Elev= 30
       0 1436.69     8.3 1435.74    33.2 1433.66    79.1 1430.43    98.6  1428.7
   108.3 1428.27  114.35 1428.74   117.1 1428.96   127.8 1430.67   147.3  1434.2
     157  1435.7   176.5 1438.46     196  1440.6   205.8  1441.5   215.5 1442.09
   254.5 1443.94     274 1445.18     313 1448.45  347.751451.775   381.2    1455
   400.7 1457.42  411.391459.039   449.4 1465.62     469 1469.33   478.7 1471.43
   498.2 1476.12   537.2 1486.39   556.7 1491.13   566.4 1493.11   605.4 1499.67
#Mann= 6 ,-1 , 0
       0     .12       0    98.6    .045       0  114.35    .045       0
   117.1     .12       0  347.75    .016       0  411.39     .12       0
Bank Sta=98.6,114.35
XS Rating Curve= 0 ,0
Exp/Cntr=0.3,0.1

Type RM Length L Ch R = 1 ,3119.9  ,335.4,377.3,418.3
XS GIS Cut Line= 4
     1860452.344      241223.841     1860421.535      241377.885
     1860650.702      241482.051     1860631.737      241767.635
#Sta/Elev= 30
       0 1446.97   30.881442.077    39.3 1440.96    58.9 1439.73    68.7 1438.67
     108 1431.49   127.6 1429.24   157.1 1426.94  187.231427.182   205.5 1427.33
   215.2 1426.72  242.26 1422.33   253.9 1421.78  259.17 1422.36     261 1422.56
  269.571424.075     283 1426.73   292.6  1427.8  340.011429.176  377.831430.756
   408.8  1432.6  433.561431.963     447 1432.28   466.1 1434.71   485.2 1438.59
   532.8 1450.17   561.5 1458.62   580.6 1464.63   637.8 1484.15     695 1502.49
#Mann= 11 ,-1 , 0
       0    .016       0   30.88     .12       0  187.23     .06       0
   205.5     .12       0  242.26    .045       0  259.17    .045       0
     261     .12       0  269.57     .06       0  340.01     .12       0
  377.83    .016       0  433.56     .12       0
Bank Sta=242.26,259.17
XS Rating Curve= 0 ,0
Exp/Cntr=0.3,0.1

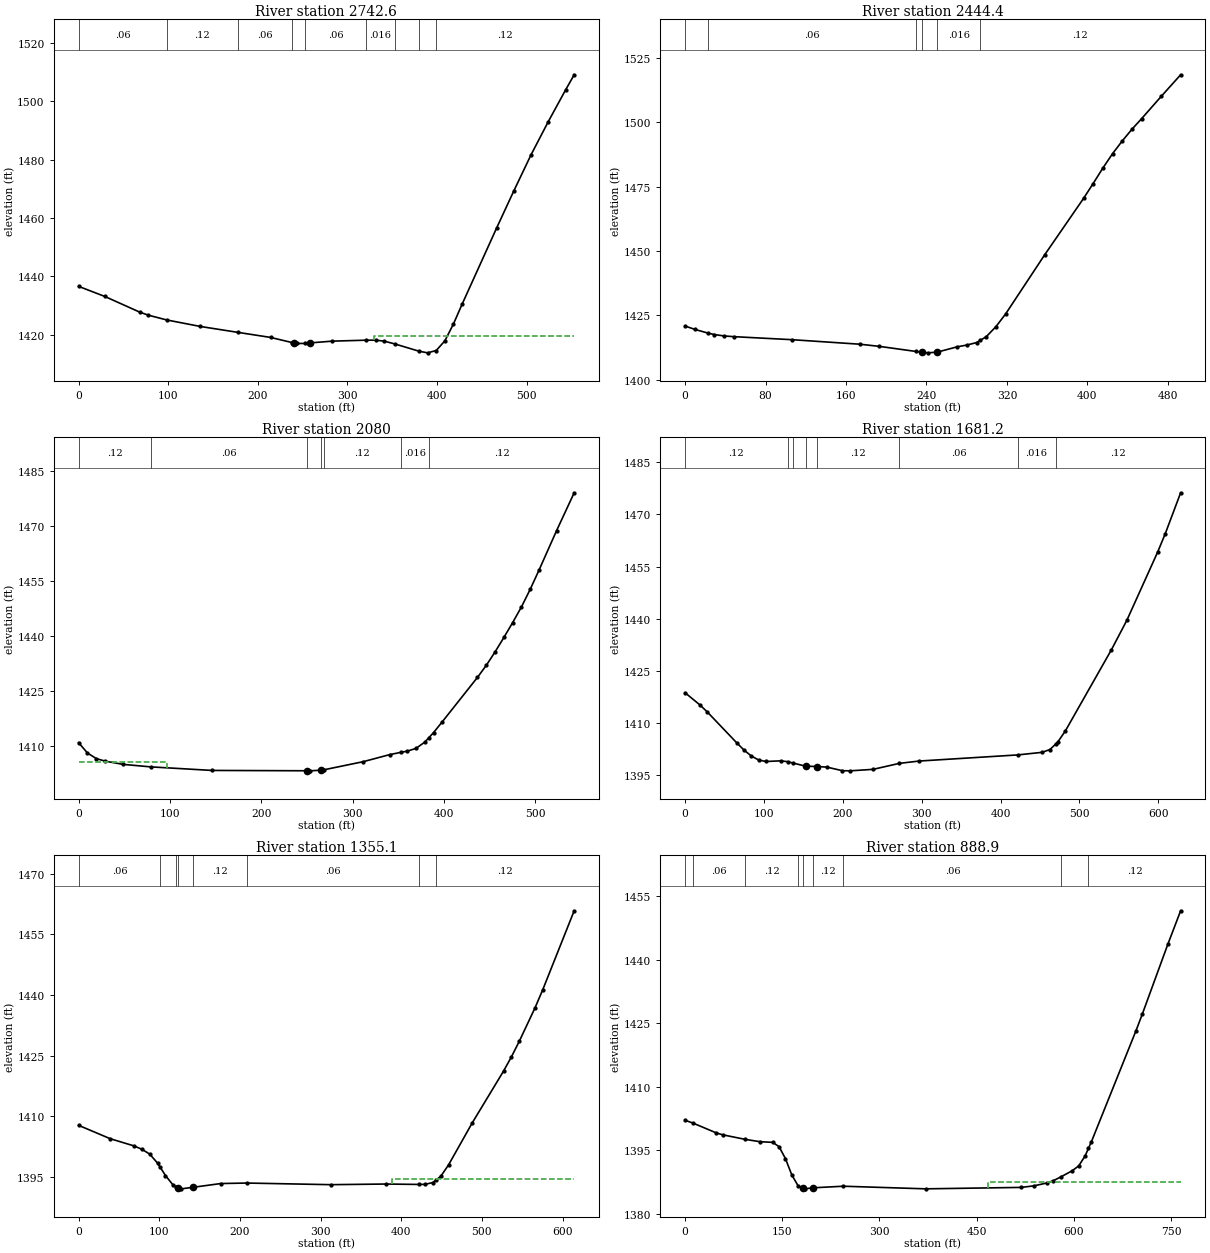
Type RM Length L Ch R = 1 ,2742.6  ,304.5,298.2,291.6
XS GIS Cut Line= 4
     1860290.494      241244.975     1860252.264      241415.645
     1860159.816      241530.228     1860107.932      241755.385
#Sta/Elev= 30
       0  1436.6    29.2 1433.15      68 1427.81    77.7 1426.75   98.411425.101
     136 1422.87  177.791420.857   214.2 1419.13   238.1 1417.38  240.11  1417.3
   243.6 1417.05   253.1 1417.07  257.98 1417.24   282.9 1417.85  320.371418.178
   331.8 1418.19   341.4 1417.84  353.471416.851   379.9 1414.42   389.5 1413.85
   399.2 1414.65   408.8 1417.94   418.4 1423.71     428 1430.44   466.5 1456.49
   485.8 1469.26     505  1481.6   524.3 1492.99   543.6 1503.83   553.2 1509.02
#Mann= 9 ,-1 , 0
       0     .06       0   98.41     .12       0  177.79     .06       0
   238.1    .045       0   253.1     .06       0  320.37    .016       0
  353.47     .12       0   379.9    .045       0   399.2     .12       0
#XS Ineff= 2 , 0
                          330.26         1419.69
Permanent Ineff=
       F       F
Bank Sta=240.11,257.98
XS Rating Curve= 0 ,0
Exp/Cntr=0.3,0.1

Type RM Length L Ch R = 1 ,2444.4  ,360.9,364.4,367.6
XS GIS Cut Line= 2
     1860011.468      241207.493     1859818.009      241660.722
#Sta/Elev= 30
       0 1420.82     9.7 1419.52   22.291418.129      29 1417.52    38.6 1416.98
    48.3  1416.7   106.3 1415.52   173.9 1413.76   193.2 1412.92  229.571410.949
   235.9 1410.64   241.6 1410.41   250.9  1410.7   270.6 1412.75   280.2 1413.43
   289.9  1414.4  293.411415.234   299.5 1416.68   309.2 1420.61   318.9 1425.61
   357.5 1448.44   396.2 1470.38   405.8 1476.18   415.5 1482.22   425.2 1487.84
   434.8 1492.76   444.5 1497.32   454.1 1501.43   473.5 1510.04   492.8 1518.43
#Mann= 6 ,-1 , 0
       0     .12       0   22.29     .06       0  229.57     .12       0
   235.9    .045       0   250.9    .016       0  293.41     .12       0
Bank Sta=235.9,250.9
XS Rating Curve= 0 ,0
Exp/Cntr=0.3,0.1

Type RM Length L Ch R = 1 ,2080    ,411.1,398.8,385.8
XS GIS Cut Line= 3
      1859732.87      241038.523     1859563.896       241311.84
     1859534.098      241531.203
#Sta/Elev= 30
       0 1410.97     9.7 1408.14    19.5 1406.62    29.2 1405.93    48.7 1405.06
   78.751404.383   146.1 1403.41  249.58 1403.32   253.2  1403.3  265.82 1403.48
   268.4 1403.57   311.6 1405.79   340.6 1407.71  353.061408.341   359.8 1408.65
   369.5 1409.42   379.1 1411.12  383.581412.329   388.7 1413.71   398.3 1416.67
   436.8 1428.74   446.5 1432.04   456.1 1435.68   465.7  1439.6   475.3 1443.64
     485 1447.94   494.6 1452.74   504.2 1457.94   523.5 1468.72   542.7 1478.99
#Mann= 7 ,-1 , 0
       0     .12       0   78.75     .06       0  249.58    .045       0
  265.82    .045       0   268.4     .12       0  353.06    .016       0
  383.58     .12       0
#XS Ineff= 2 , 0
           97.21 1405.68
Permanent Ineff=
       F       F
Bank Sta=249.58,265.82
XS Rating Curve= 0 ,0
Exp/Cntr=0.3,0.1

Type RM Length L Ch R = 1 ,1681.2  ,317.4,326.2,333.3
XS GIS Cut Line= 3
     1859353.029      240881.184     1859284.382      240981.328
     1859271.508      241488.155
#Sta/Elev= 30
       0 1418.68    18.7 1415.19      28 1413.19    65.4 1404.29    74.7 1402.19
    84.1 1400.46    93.4 1399.32   102.7  1398.9   121.4 1399.09  130.041398.843
  137.061398.442   152.7 1397.56   167.7 1397.45   179.9 1397.28   199.4 1396.25
   209.2 1396.21   238.4 1396.64  271.831398.365   296.9 1399.03  421.591400.787
   452.9 1401.54   462.7 1402.35  469.741403.867   472.4 1404.44   482.2 1407.69
   540.7 1431.08   560.2 1439.53   599.2 1459.13   608.9 1464.45   628.4 1476.22
#Mann= 8 ,-1 , 0
       0     .12       0  130.04     .06       0  137.06     .12       0
   152.7    .045       0   167.7     .12       0  271.83     .06       0
  421.59    .016       0  469.74     .12       0
Bank Sta=152.7,167.7
XS Rating Curve= 0 ,0
Exp/Cntr=0.3,0.1

Type RM Length L Ch R = 1 ,1355.1  ,475.4,466.1,455.7
XS GIS Cut Line= 3
     1859021.969      240846.754      1858945.84      241037.752
     1858947.203      241446.585
#Sta/Elev= 30
       0 1407.77    39.2 1404.46    68.5 1402.69    78.3 1401.86    88.1 1400.66
    97.9 1398.42  101.171397.392   107.7 1395.34   117.5  1392.9   120.9 1392.61
  123.49 1392.38   127.3 1392.06  141.53 1392.43   176.2 1393.37  208.541393.493
   312.7 1393.09   380.8 1393.25  422.311393.148   429.5 1393.17   439.2 1393.62
  442.521394.142     449 1395.16   458.7    1398   487.9 1408.34   526.8 1421.18
   536.6 1424.71   546.3 1428.55   565.8 1436.81   575.5 1441.35   614.4 1460.85
#Mann= 8 ,-1 , 0
       0     .06       0  101.17     .12       0   120.9    .045       0
  123.49    .045       0  141.53     .12       0  208.54     .06       0
  422.31    .016       0  442.52     .12       0
#XS Ineff= 2 , 0
                          387.93         1394.46
Permanent Ineff=
       F       F
Bank Sta=123.49,141.53
XS Rating Curve= 0 ,0
Exp/Cntr=0.3,0.1

Type RM Length L Ch R = 1 ,888.9   ,491.5,496,497.6
XS GIS Cut Line= 3
     1858686.284      240804.088     1858565.277      240836.709
     1858615.016      241474.268
#Sta/Elev= 30
       0 1402.06   11.931401.408    48.2 1399.07    57.8 1398.63   92.881397.543
   115.7 1396.99   135.2 1396.84     145 1395.82   154.8 1393.02   164.7 1389.13
     175 1386.41   182.1 1385.99   184.4 1385.85     197 1386.09  244.311386.469
   371.3 1385.85   518.9 1386.19   538.5 1386.56   558.2 1387.23     568 1387.75
  580.871388.753   597.6 1390.14   607.4 1391.26   617.2 1393.58  622.551395.423
   627.1 1396.99     696 1423.27   705.8 1427.22   745.2 1443.73   764.8 1451.58
#Mann= 9 ,-1 , 0
       0     .12       0   11.93     .06       0   92.88     .12       0
     175    .045       0   182.1    .045       0     197     .12       0
  244.31     .06       0  580.87    .016       0  622.55     .12       0
#XS Ineff= 2 , 0
                          468.11         1387.57
Permanent Ineff=
       F       F
Bank Sta=182.1,197
XS Rating Curve= 0 ,0
Exp/Cntr=0.3,0.1

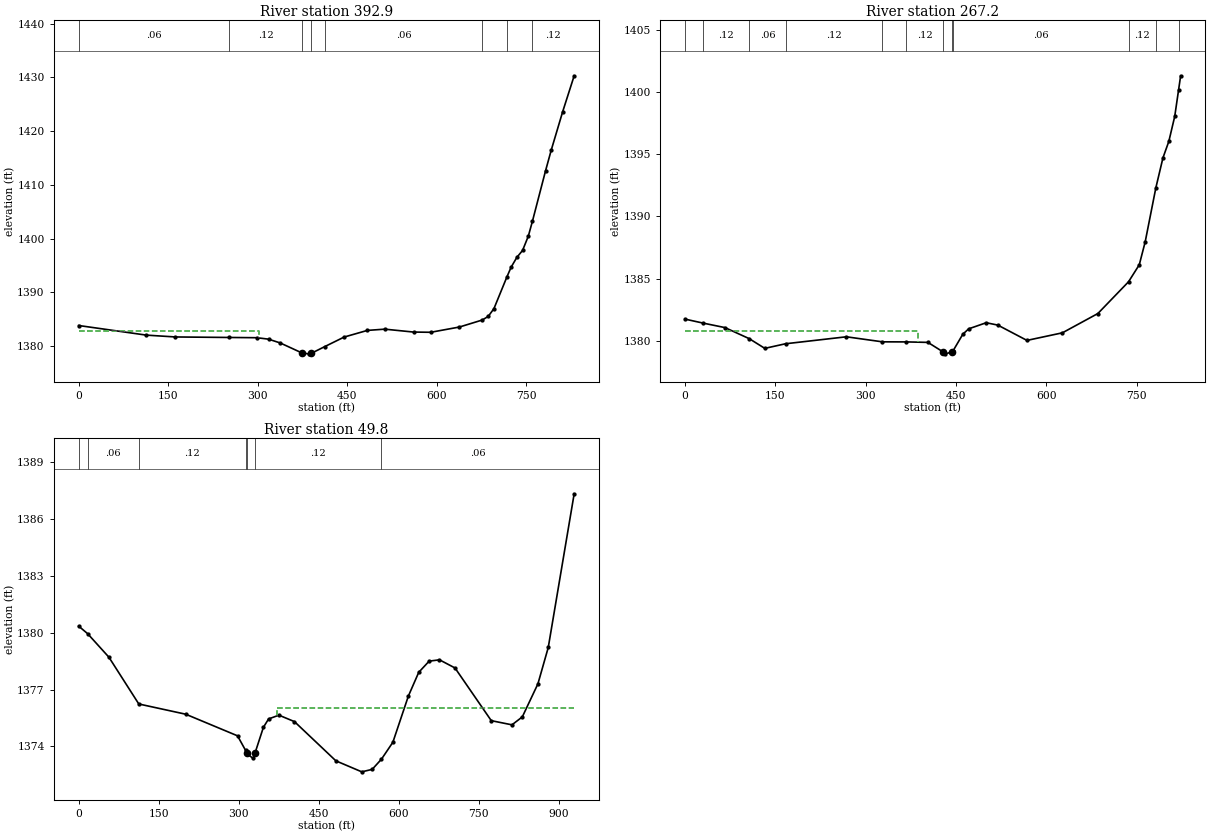
Type RM Length L Ch R = 1 ,392.9   ,128.8,125.7,122.2
XS GIS Cut Line= 4
     1858350.615      240808.917     1858241.004      240837.903
     1858230.563      241246.953     1858417.824        241490.7
#Sta/Elev= 30
       0 1383.83   113.4 1382.04   162.1  1381.7  252.291381.605   298.5 1381.56
     318 1381.29   337.5 1380.59   374.9 1378.68   386.2 1378.56   389.9 1378.67
  412.09  1379.9   444.6 1381.68   483.6 1382.92   512.8 1383.15     561 1382.61
   589.8 1382.57   637.8 1383.55  675.981384.852   685.9 1385.52   695.5 1386.96
  717.041392.812   724.3 1394.68   733.9  1396.5   743.5  1397.8   753.1 1400.45
     7601403.224   781.9 1412.58   791.5 1416.46   810.7 1423.62   829.9 1430.28
#Mann= 8 ,-1 , 0
       0     .06       0  252.29     .12       0   374.9    .045       0
   389.9     .12       0  412.09     .06       0  675.98     .12       0
  717.04    .016       0     760     .12       0
#XS Ineff= 2 , 0
          301.34 1382.89
Permanent Ineff=
       F       F
Bank Sta=374.9,389.9
XS Rating Curve= 0 ,0
Exp/Cntr=0.3,0.1

Type RM Length L Ch R = 1 ,267.2   ,207.1,217.4,226.6
XS GIS Cut Line= 4
     1858211.759      240822.199     1858083.463      240854.838
     1858136.898      241287.064     1858285.413      241494.744
#Sta/Elev= 30
       0 1381.75   29.671381.433    66.2 1381.07  106.591380.179   132.4  1379.4
  166.81 1379.77   267.9 1380.33  327.791379.925  367.681379.919   403.4 1379.88
  428.73 1379.11   432.4 1378.96  444.05 1379.12     445 1379.19   461.4 1380.54
   471.1 1380.97   500.2 1381.46   519.5 1381.27   567.9 1380.04   626.8 1380.65
   685.7  1382.2  736.631384.752   754.5 1386.12   764.3 1387.96  782.051392.311
   793.8 1394.71   803.6 1396.04   813.4 1398.05  819.671400.136   823.2 1401.31
#Mann= 12 ,-1 , 0
       0     .06       0   29.67     .12       0  106.59     .06       0
  166.81     .12       0  327.79     .06       0  367.68     .12       0
  428.73    .045       0  444.05    .045       0     445     .06       0
  736.63     .12       0  782.05    .016       0  819.67     .12       0
#XS Ineff= 2 , 0
             387 1380.78
Permanent Ineff=
       F       F
Bank Sta=428.73,444.05
XS Rating Curve= 0 ,0
Exp/Cntr=0.3,0.1

Type RM Length L Ch R = 1 ,49.8    ,51.1,49.8,48.5
XS GIS Cut Line= 4
     1858128.446       240817.37      1858017.94      240842.905
     1857877.264        241297.3      1858119.16      241536.034
#Sta/Elev= 30
       0 1380.35   16.911379.948    56.7 1378.71   112.8 1376.24   200.8  1375.7
   297.9 1374.56     313 1373.79  314.91 1373.63     327 1373.37  330.67 1373.65
   346.4 1375.01   356.1 1375.45   375.5 1375.65   404.6 1375.31   482.3 1373.24
   530.8 1372.66   550.3 1372.79  567.77 1373.33   589.1 1374.22   618.2 1376.66
   637.6 1377.91   657.1  1378.5   676.5 1378.57   705.6 1378.14   773.6 1375.36
   812.4 1375.14   831.8 1375.56     861  1377.3   880.4 1379.22     929 1387.33
#Mann= 7 ,-1 , 0
       0     .12       0   16.91     .06       0   112.8     .12       0
     313    .045       0  314.91    .045       0  330.67     .12       0
  567.77     .06       0
#XS Ineff= 2 , 0
                          372.55         1376.05
Permanent Ineff=
       F       F
Bank Sta=314.91,330.67
XS Rating Curve= 0 ,0
Exp/Cntr=0.3,0.1
LCMann Table=0

Chan Stop Cuts=-1
Use User Specified Reach Order=0
Composite Channel Slope=5